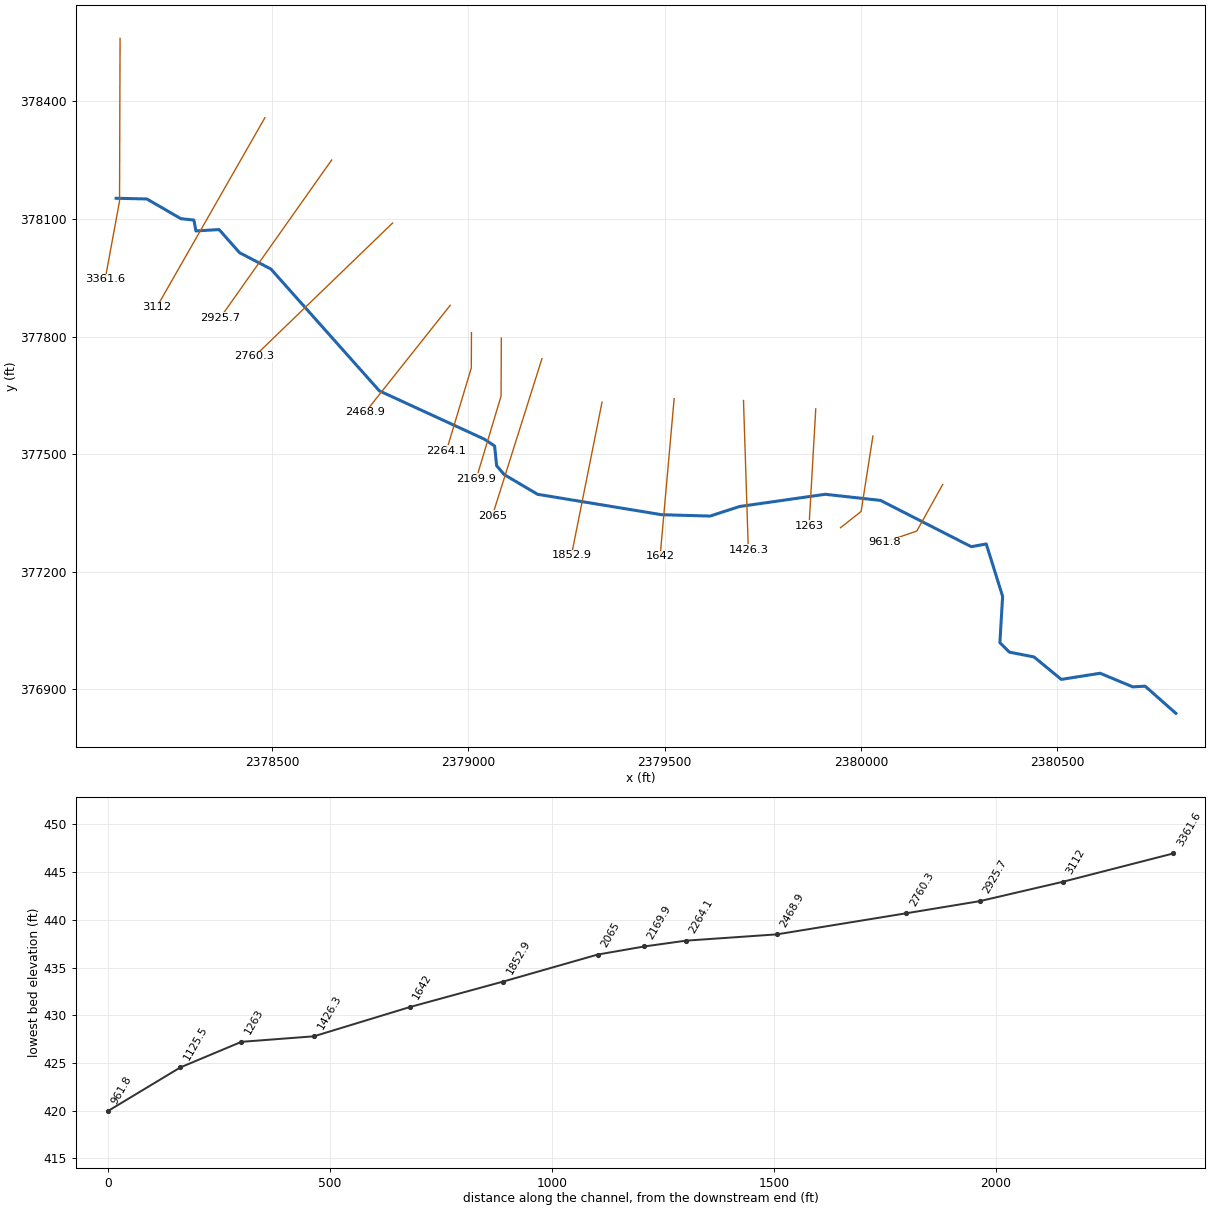
--- TOMAHAWKRN.prj (project) ---

Proj Title=TOMAHAWKRN
Current Plan=p01
Default Exp/Contr=0,0
English Units
Geom File=g01
Flow File=f01
Plan File=p01
BEGIN DESCRIPTION:
END DESCRIPTION:
DSS Export Rating Curves= 0
DSS Export Rating Curve Sorted= 0
DSS Export Volume Flow Curves= 0
DXF OffsetX= 0
DXF OffsetY= 0
DXF ScaleX= 0
DXF ScaleY= 0

--- TOMAHAWKRN.p01 (plan) ---

Plan Title=Floodplain
Program Version=4.00
Geom File=g01
Flow File=f01
K Sum by GR=0
Std Step Tol=0.01
Critical Tol=0.01
Num of Std Step Trials=20
Max Error Tol=0.3
Flow Tol Ratio=0.001
Split Flow NTrial=30
Split Flow Tol=0.02
Split Flow Ratio=0.02
Log Output Level=0
Friction Slope Method=1
Unsteady Friction Slope Method=2
Unsteady Bridges Friction Slope Method=1
Global Log Level=0
CheckData=False
Run HTab=0
Run UNet=0
Run PostProcess=0
UNET Theta=0
UNET Theta Warmup=0
UNET ZTol=0
UNET ZSATol=0
UNET MxIter=0
UNET MaxInSteps=0
UNET DtIC=0
UNET DtMin=0
UNET MaxCRTS=0
UNET WFStab=0
UNET SFStab=0
UNET WFX=0
UNET SFX=0
UNET DSS MLevel=0
UNET DZMax Abort=0
UNET Convert EG Bridges=0
UNET Use Existing IB Tables=0
UNET Froude Limit=0
UNET Froude Power=0
Write IC File=0
Echo Input=False
Echo Output=False
Write Detailed=0

--- TOMAHAWKRN.f01 (steady flow) ---

Flow Title=NFF Regression Equation
Program Version=4.00
Number of Profiles=1
Profile Names=P100yr
River Rch & RM=TOMAHAWKRN,Main      ,3361.6
553.9535
River Rch & RM=TOMAHAWKRN,Main      ,3112
646.7371
Boundary for River Rch & Prof#=TOMAHAWKRN,Main      ,1
Up Type=0
Dn Type=3
Dn Slope=0.017027

--- TOMAHAWKRN.g01 (geometry) ---

Geom Title=USGS 10m DEM
Program Version=4.10

River Reach=TOMAHAWKRN      ,Main
Reach XY= 30
     2378103.453      378153.092     2378181.578      378151.356
     2378268.384      378101.009      2378301.37      378097.536
     2378306.578      378069.759     2378365.606      378073.231
      2378417.69      378014.203     2378497.551      377972.536
     2378773.592      377661.773     2379040.953      377538.509
     2379066.995      377521.147     2379072.203        377470.8
       2379091.3      377448.231      2379176.37      377397.884
     2379492.342        377345.8     2379615.606      377342.328
     2379690.259      377366.634     2379909.009      377397.884
     2380049.634      377382.259     2380280.537      377264.203
     2380318.731      377271.148     2380360.398      377137.467
     2380353.453      377019.411     2380377.759      376995.106
     2380440.259      376982.953     2380509.703      376925.661
     2380608.662      376941.286     2380691.995      376906.564
     2380723.245        376908.3     2380801.611      376838.957

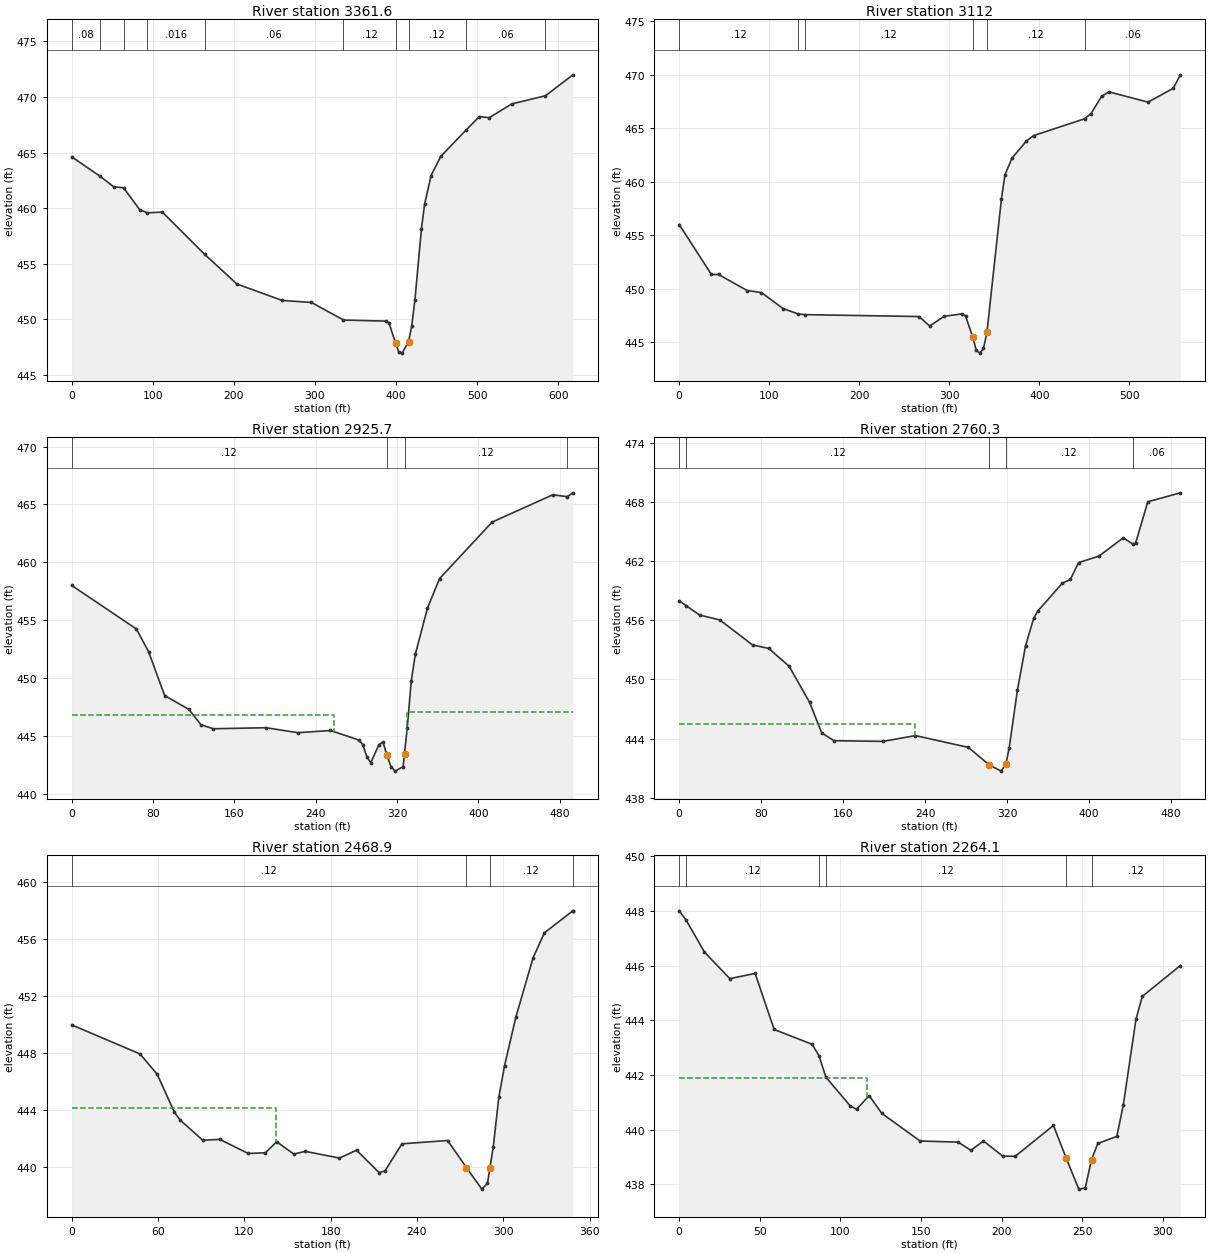
Type RM Length L Ch R = 1 ,3361.6  ,262.2,249.7,251.8
XS GIS Cut Line= 3
     2378113.453      378561.127     2378112.109      378145.768
     2378075.511      377946.324
#Sta/Elev= 30
       0  464.62   34.36462.9042    51.9  461.92   63.88461.8403    83.9  459.86
    93.4459.5823   111.8  459.65  164.14 455.836   203.7  453.18   259.6   451.7
   295.6  451.52  335.17449.9382   387.4  449.84   391.4  449.66   399.4  447.85
   403.4  447.05   407.4  446.96   415.4     448   419.3  449.41   423.3  451.78
   431.3  458.14   435.2  460.37   443.2  462.94   455.1  464.66  485.85466.9965
   502.8  468.25   514.8  468.14   542.6  469.38  584.28470.1175   618.1     472
#Mann= 10 ,-1 , 0
       0     .08       0   34.36     .06       0   63.88     .08       0
    93.4    .016       0  164.14     .06       0  335.17     .12       0
   399.4    .045       0   415.4     .12       0  485.85     .06       0
  584.28     .12       0
Bank Sta=399.4,415.4
XS Rating Curve= 0 ,0
Exp/Cntr=0.3,0.1

Type RM Length L Ch R = 1 ,3112    ,189.7,186.3,179.7
XS GIS Cut Line= 2
       2378482.1      378358.523     2378206.583      377875.006
#Sta/Elev= 30
       0     456    35.8  451.33    43.7  451.33    75.5  449.83    91.4  449.64
   115.3  448.15  132.04447.6437  139.48447.5781   266.3   447.4   278.2  446.51
   294.2  447.42     314  447.65     318  447.45     326  445.48   329.9  444.24
   333.9  443.98   337.9  444.42   341.8  445.96   357.8  458.37   361.7  460.64
   369.7  462.22   385.6  463.81   393.5  464.31  450.13465.8811   457.1  466.35
     469  467.97     477   468.4   520.7  467.44   548.6  468.73   556.5  469.99
#Mann= 6 ,-1 , 0
       0     .12       0  132.04     .06       0  139.48     .12       0
     326    .045       0   341.8     .12       0  450.13     .06       0
Bank Sta=326,341.8
XS Rating Curve= 0 ,0
Exp/Cntr=0.3,0.1

Type RM Length L Ch R = 1 ,2925.7  ,169.7,165.4,161
XS GIS Cut Line= 2
     2378652.114      378250.734     2378368.114      377847.704
#Sta/Elev= 30
       0     458    63.6  454.24    75.6  452.28    91.4  448.49   115.3  447.29
   127.2  445.96   139.2  445.62   190.8  445.71   222.7  445.28   254.5  445.47
   282.3  444.65   286.3  444.26   290.3   443.2   294.2  442.69   302.2  444.25
   306.2  444.45   310.1  443.33   314.1  442.33   318.1  441.96     326  442.35
  327.35  443.48     330  445.68     334  449.76     338  452.06   349.9  456.03
   361.8  458.59   413.5  463.47   473.2  465.83  487.37465.6686     493     466
#Mann= 4 ,-1 , 0
       0     .12       0   310.1    .045       0  327.35     .12       0
  487.37     .06       0
#XS Ineff= 2 , 0
          258.39  446.78  329.43          447.08
Permanent Ineff=
       F       F
Bank Sta=310.1,327.35
XS Rating Curve= 0 ,0
Exp/Cntr=0.3,0.1

Type RM Length L Ch R = 1 ,2760.3  ,288.3,291.4,294.3
XS GIS Cut Line= 2
     2378807.303      378089.966     2378455.676      377749.682
#Sta/Elev= 30
       0     458    6.86 457.494    19.9  456.55    39.8  456.04    71.6  453.51
    87.5  453.15   107.4  451.34   127.3  447.68   139.2  444.57   151.2  443.78
   198.9  443.71   230.7   444.3   282.4   443.1   302.3  441.35   314.3  440.69
  318.91  441.39   322.2  443.05   330.2  448.92   338.2  453.43   346.1  456.21
   350.1  456.95     374  459.77   381.9  460.16   389.9  461.87   409.8  462.53
   433.6  464.39  442.97463.7448   445.6  463.85   457.5  468.05   489.3  468.96
#Mann= 5 ,-1 , 0
       0     .06       0    6.86     .12       0   302.3    .045       0
  318.91     .12       0  442.97     .06       0
#XS Ineff= 2 , 0
          229.79  445.48
Permanent Ineff=
       F       F
Bank Sta=302.3,318.91
XS Rating Curve= 0 ,0
Exp/Cntr=0.3,0.1

Type RM Length L Ch R = 1 ,2468.9  ,196,204.8,213.6
XS GIS Cut Line= 2
     2378954.025      377880.071     2378737.675      377606.976
#Sta/Elev= 30
       0     450    47.5  447.96    59.4  446.54    71.3  443.89    75.2  443.34
    91.1  441.91   102.9  441.97   122.7  440.98   134.6  441.03   142.5   441.8
   154.4  440.94   162.3  441.13   186.1  440.66     198  441.21   213.8  439.63
   217.8  439.77   229.6  441.66   261.3  441.89   274.4  439.99   285.1  438.48
     289  438.89  290.67  439.94     293  441.42   296.9  444.92   300.9  447.15
   308.8  450.57   320.7   454.7   328.6  456.46  348.23457.9885   348.4     458
#Mann= 4 ,-1 , 0
       0     .12       0   274.4    .045       0  290.67     .12       0
  348.23     .06       0
#XS Ineff= 2 , 0
          142.06  444.16
Permanent Ineff=
       F       F
Bank Sta=274.4,290.67
XS Rating Curve= 0 ,0
Exp/Cntr=0.3,0.1

Type RM Length L Ch R = 1 ,2264.1  ,94.2,94.2,94.3
XS GIS Cut Line= 3
     2379008.114       377810.31     2379007.613      377720.036
     2378944.337       377508.76
#Sta/Elev= 30
       0     448    4.34447.6583    15.7  446.49    31.4  445.52    47.1  445.71
    58.9  443.66    82.4  443.12   86.69442.7035   90.97441.9175     106  440.87
     110  440.74   117.8  441.24   125.7  440.59   149.4  439.58     173  439.54
   180.9  439.24   188.7  439.58   200.6  439.03   208.4  439.02   232.1  440.15
   239.9  438.97   247.8  437.82   251.8  437.86   255.7   438.9   259.6  439.49
   271.4  439.75   275.4  440.89   283.3  444.04   287.2  444.87   310.8     446
#Mann= 6 ,-1 , 0
       0     .06       0    4.34     .12       0   86.69    .016       0
   90.97     .12       0   239.9    .045       0   255.7     .12       0
#XS Ineff= 2 , 0
          116.73  441.89
Permanent Ineff=
       F       F
Bank Sta=239.9,255.7
XS Rating Curve= 0 ,0
Exp/Cntr=0.3,0.1

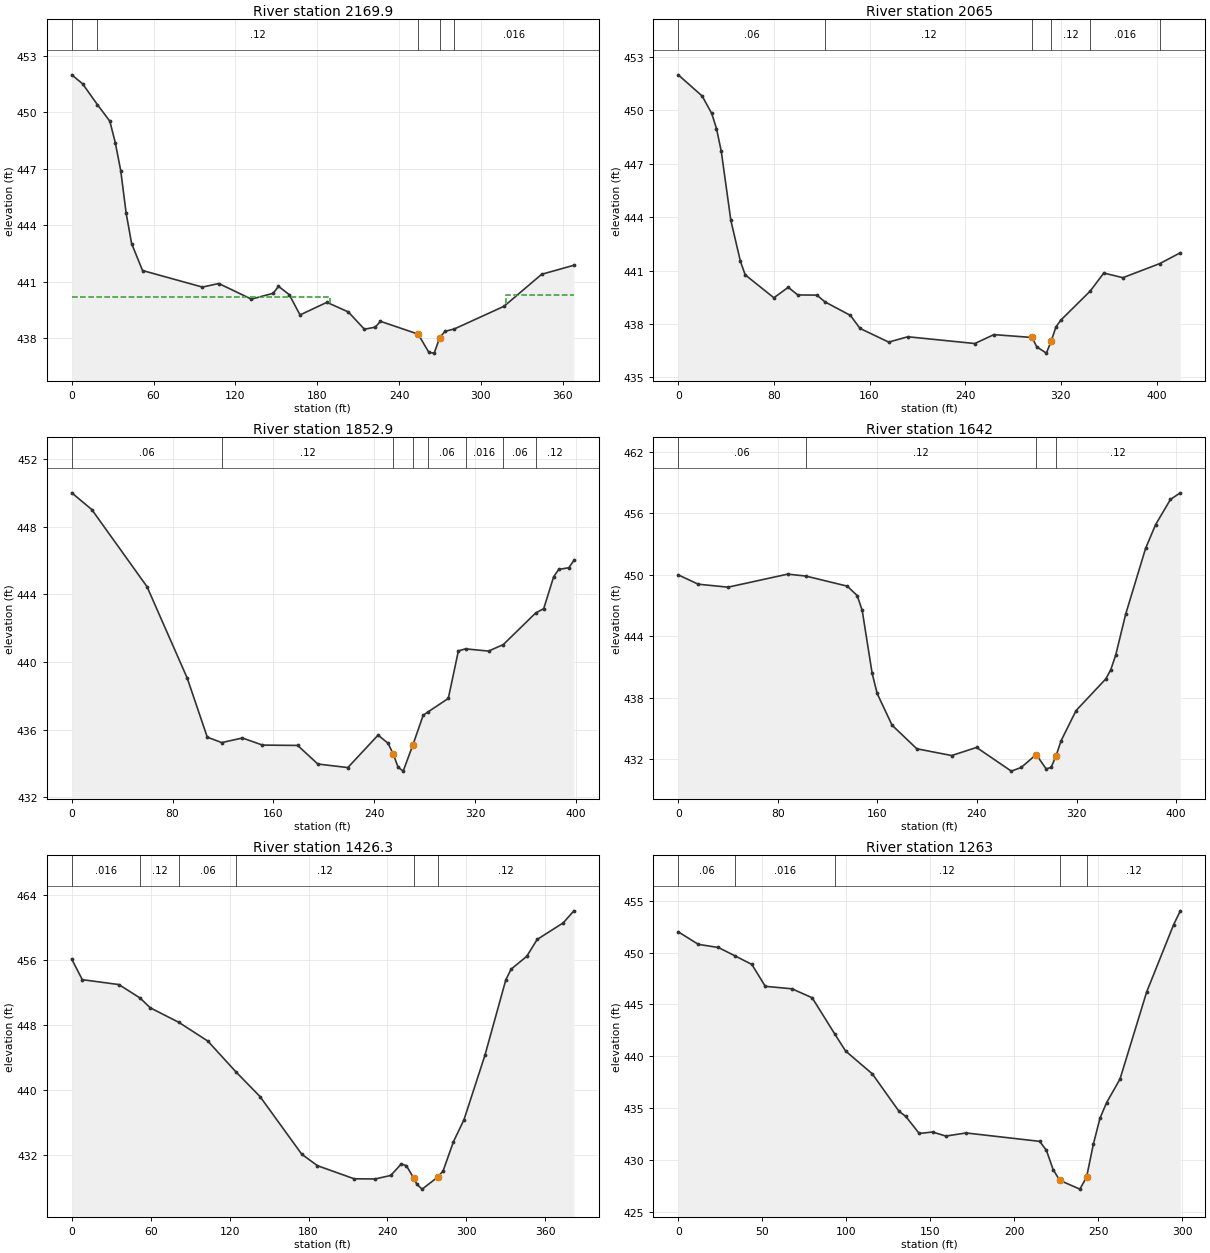
Type RM Length L Ch R = 1 ,2169.9  ,105.3,104.9,103.5
XS GIS Cut Line= 3
     2379084.114      377796.226     2379083.501      377648.548
     2379020.226      377437.272
#Sta/Elev= 30
       0     452       8  451.52   18.74450.4208    27.9  449.54    31.9   448.4
    35.9  446.91    39.9  444.64    43.9  443.03    51.9   441.6    95.8  440.72
   107.8  440.91   131.7  440.08   147.7  440.39   151.6  440.76   159.5  440.32
   167.4  439.24   187.1  439.91   202.8   439.4   214.6  438.48   222.5  438.59
   226.4   438.9     254  438.22   261.9  437.25   265.8  437.21   269.8  438.03
   273.7  438.37  280.52438.4938     317   439.7   344.6   441.4   368.2  441.88
#Mann= 5 ,-1 , 0
       0     .06       0   18.74     .12       0     254    .045       0
   269.8     .12       0  280.52    .016       0
#XS Ineff= 2 , 0
          189.26  440.18   318.6          440.28
Permanent Ineff=
       F       F
Bank Sta=254,269.8
XS Rating Curve= 0 ,0
Exp/Cntr=0.3,0.1

Type RM Length L Ch R = 1 ,2065    ,210.3,212.1,214.6
XS GIS Cut Line= 2
     2379187.504       377743.82     2379061.357      377343.295
#Sta/Elev= 30
       0     452      20  450.81      28  449.83      32  448.98      36   447.7
      44  443.82      52  441.52      56  440.76      80  439.47      92  440.06
     100  439.63     116  439.62  122.72  439.24     144  438.48     152  437.75
     176  436.98     192  437.28     248   436.9     264   437.4   295.9  437.24
   299.9  436.71   307.9  436.36   311.9  437.04   315.9  437.83   319.9  438.21
  344.49439.8434   355.9  440.86   371.9   440.6  402.74441.3936   419.9     442
#Mann= 6 ,-1 , 0
       0     .06       0  122.72     .12       0   295.9    .045       0
   311.9     .12       0  344.49    .016       0  402.74     .12       0
Bank Sta=295.9,311.9
XS Rating Curve= 0 ,0
Exp/Cntr=0.3,0.1

Type RM Length L Ch R = 1 ,1852.9  ,208.4,210.9,213.3
XS GIS Cut Line= 2
      2379340.54      377632.948     2379262.633      377242.367
#Sta/Elev= 30
       0     450    15.9  449.01    59.7  444.45    91.6  439.04   107.5  435.55
  118.95435.2286   135.4   435.5   151.3  435.08   179.2  435.06   195.2  433.96
     219  433.75     243  435.67   250.9  435.19   254.9  434.57   258.9  433.77
   262.9  433.54   270.7  435.11   278.8  436.85  282.36 437.028   298.7  437.84
   306.7  440.65  312.36 440.773   330.6  440.64  342.36441.0258  368.01442.8945
   374.4  443.15   382.3  445.04   386.3  445.47   394.3  445.57   398.3     446
#Mann= 8 ,-1 , 0
       0     .06       0  118.95     .12       0   254.9    .045       0
   270.7     .12       0  282.36     .06       0  312.36    .016       0
  342.36     .06       0  368.01     .12       0
Bank Sta=254.9,270.7
XS Rating Curve= 0 ,0
Exp/Cntr=0.3,0.1

Type RM Length L Ch R = 1 ,1642    ,212.9,215.7,218.4
XS GIS Cut Line= 2
     2379524.114       377642.05     2379488.471       377240.18
#Sta/Elev= 30
       0     450      16  449.09      40   448.8    87.9  450.07  102.54449.8838
   135.8   448.9   143.8  447.98   147.8  446.54   155.8   440.4   159.8  438.44
   171.8  435.34   191.7  433.04   219.7  432.38   239.7  433.17   267.6  430.86
   275.6  431.22   287.6  432.48   295.6  431.08   299.6  431.22   303.6  432.37
   307.6  433.82   319.6  436.76   343.5  439.85   347.5  440.74   351.5  442.18
   359.5  446.17   375.5  452.58   383.5  454.89   395.5  457.36   403.4     458
#Mann= 4 ,-1 , 0
       0     .06       0  102.54     .12       0   287.6    .045       0
   303.6     .12       0
Bank Sta=287.6,303.6
XS Rating Curve= 0 ,0
Exp/Cntr=0.3,0.1

Type RM Length L Ch R = 1 ,1426.3  ,165.4,163.3,161.2
XS GIS Cut Line= 2
     2379700.679      377637.102     2379713.008      377255.644
#Sta/Elev= 30
       0  456.05       8  453.54    35.8  452.94   51.89451.2906    59.6  450.09
   81.44448.2917   103.4     446  124.74442.2213   143.1  439.18   174.9  432.08
   186.8  430.68   214.7  429.07   230.6  429.05   242.5  429.48   250.5  430.89
   254.4  430.68   259.9  429.18   262.4  428.38   266.4   427.8   278.3  429.29
   282.3  430.04   290.2  433.64   298.2  436.34   314.1  444.25     330  453.53
     334  454.83   345.9  456.41   353.8  458.48   373.7  460.53   381.7     462
#Mann= 6 ,-1 , 0
       0    .016       0   51.89     .12       0   81.44     .06       0
  124.74     .12       0   259.9    .045       0   278.3     .12       0
Bank Sta=259.9,278.3
XS Rating Curve= 0 ,0
Exp/Cntr=0.3,0.1

Type RM Length L Ch R = 1 ,1263    ,139.6,137.5,135.3
XS GIS Cut Line= 2
     2379884.664      377615.987     2379867.616      377317.725
#Sta/Elev= 30
       0     452      12  450.79    23.9  450.49    33.8449.6831    43.8  448.86
    51.8  446.75    67.7  446.51    79.7  445.65   93.32442.1169    99.6  440.52
   115.5  438.32   131.4  434.71   135.4  434.23   143.4  432.58   151.4  432.72
   159.3  432.33   171.3  432.63   215.1  431.82   219.1  430.96   223.1  429.11
     227  428.07     239  427.22     243  428.36     247  431.52     251  434.05
   254.9  435.54   262.9  437.82   278.8  446.22   294.8  452.68   298.8  454.02
#Mann= 5 ,-1 , 0
       0     .06       0    33.8    .016       0   93.32     .12       0
     227    .045       0     243     .12       0
Bank Sta=227,243
XS Rating Curve= 0 ,0
Exp/Cntr=0.3,0.1

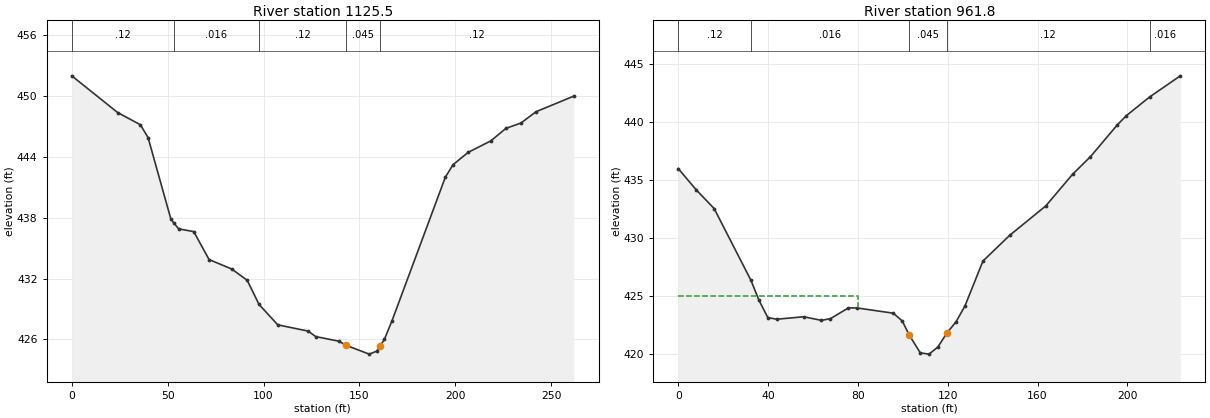
Type RM Length L Ch R = 1 ,1125.5  ,171.6,163.7,155.7
XS GIS Cut Line= 3
     2380030.154      377546.577     2380000.114      377354.056
     2379947.554      377312.537
#Sta/Elev= 30
       0     452    23.9  448.38    35.8  447.17    39.8   445.9    51.7  437.85
   53.17437.5009    55.7   436.9    63.6  436.63    71.6  433.87    83.5  432.93
    91.5  431.82   97.63429.4464   107.4  427.43   123.3  426.81   127.2  426.27
   139.2  425.82   143.2   425.4   155.1  424.54   159.1  424.84  160.96  425.39
     163  425.99     167  427.84   194.8     442   198.8  443.23   206.7  444.45
   218.5  445.58   226.4  446.82   234.2  447.34   242.1  448.46   261.8     450
#Mann= 5 ,-1 , 0
       0     .12       0   53.17    .016       0   97.63     .12       0
   143.2    .045       0  160.96     .12       0
Bank Sta=143.2,160.96
XS Rating Curve= 0 ,0
Exp/Cntr=0.3,0.1

Type RM Length L Ch R = 1 ,961.8   ,969.7,961.8,961.2
XS GIS Cut Line= 3
     2380207.823      377422.861     2380141.947      377304.241
     2380058.917      377275.339
#Sta/Elev= 30
       0     436       8  434.16      16  432.54   32.41426.3227    35.9  424.63
    39.9  423.11    43.9  422.97    55.9  423.18    63.8  422.87    67.8  423.02
    75.8  423.95    79.8  423.94    95.8  423.49    99.8  422.81  102.81  421.62
   107.8  420.06   111.7  419.95   115.6  420.56   119.7  421.79   123.7  422.74
   127.7  424.12   135.7     428   147.7  430.24   163.7  432.77   175.6   435.5
   183.6  437.03   195.6  439.79   199.6  440.58  209.89442.1864   223.6  444.02
#Mann= 5 ,-1 , 0
       0     .12       0   32.41    .016       0  102.81    .045       0
   119.7     .12       0  209.89    .016       0
#XS Ineff= 2 , 0
           80.27  424.94
Permanent Ineff=
       F       F
Bank Sta=102.81,119.7
XS Rating Curve= 0 ,0
Exp/Cntr=0.3,0.1

Chan Stop Cuts=-1
Use User Specified Reach Order=0
Composite Channel Slope=5